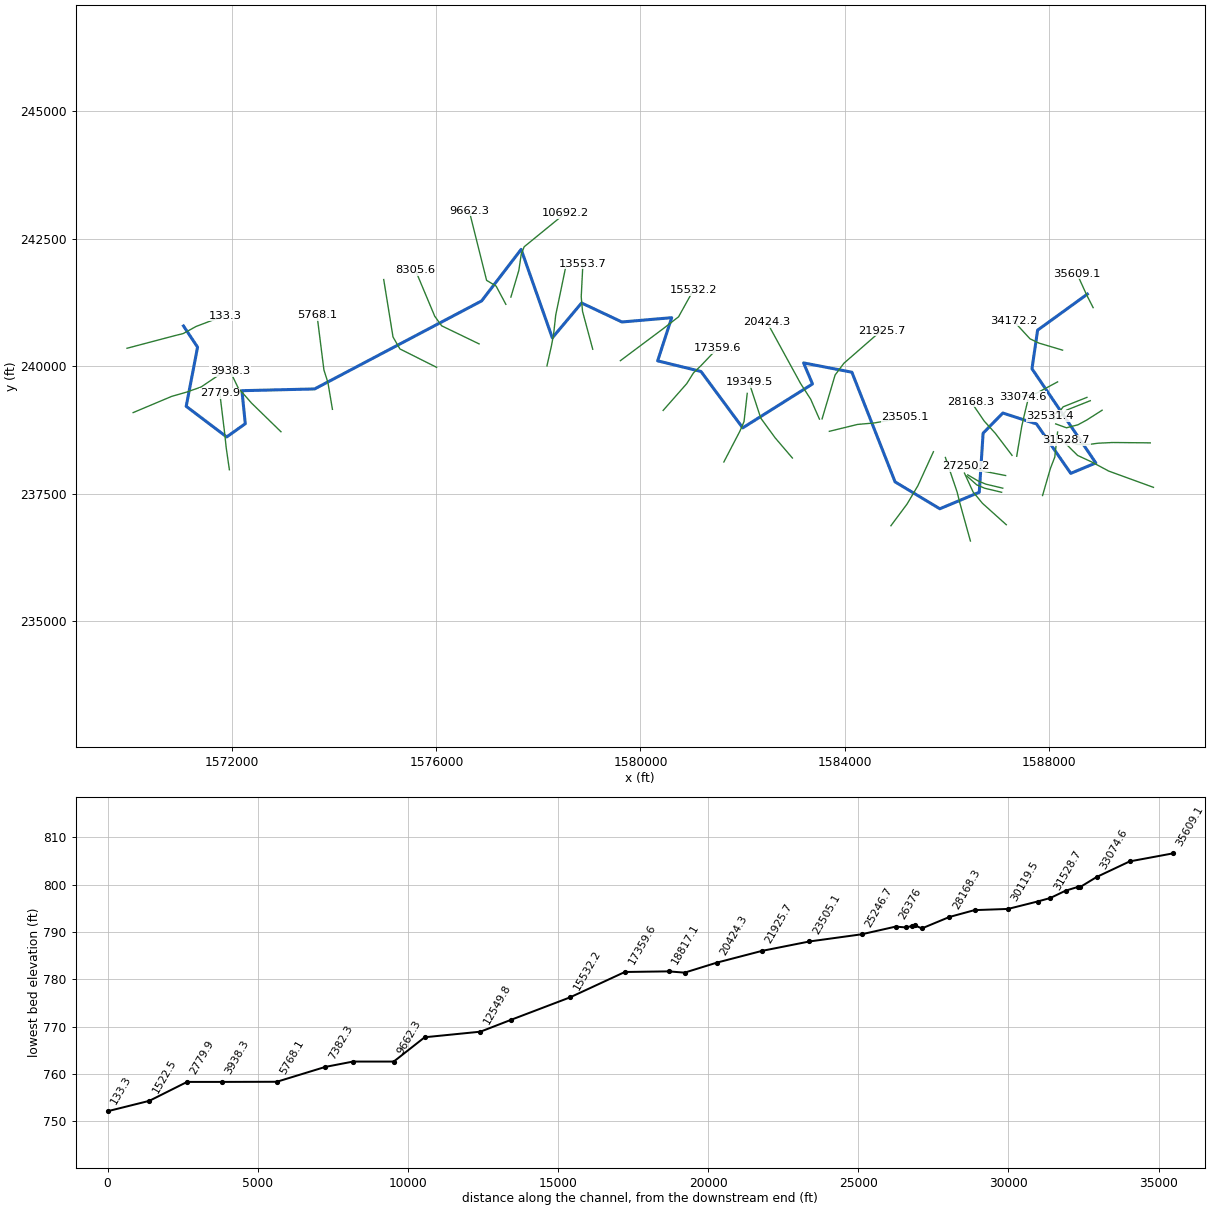
--- MDDLFR.prj (project) ---

Proj Title=MDDLFR
Current Plan=p01
Default Exp/Contr=0,0
English Units
Geom File=g01
Flow File=f01
Plan File=p01
BEGIN DESCRIPTION:
END DESCRIPTION:
DSS Export Rating Curves= 0
DSS Export Rating Curve Sorted= 0
DSS Export Volume Flow Curves= 0
DXF OffsetX= 0
DXF OffsetY= 0
DXF ScaleX= 0
DXF ScaleY= 0

--- MDDLFR.p01 (plan) ---

Plan Title=Floodplain
Program Version=4.00
Geom File=g01
Flow File=f01
K Sum by GR=0
Std Step Tol=0.01
Critical Tol=0.01
Num of Std Step Trials=20
Max Error Tol=0.3
Flow Tol Ratio=0.001
Split Flow NTrial=30
Split Flow Tol=0.02
Split Flow Ratio=0.02
Log Output Level=0
Friction Slope Method=1
Unsteady Friction Slope Method=2
Unsteady Bridges Friction Slope Method=1
Global Log Level=0
CheckData=False
Run HTab=0
Run UNet=0
Run PostProcess=0
UNET Theta=0
UNET Theta Warmup=0
UNET ZTol=0
UNET ZSATol=0
UNET MxIter=0
UNET MaxInSteps=0
UNET DtIC=0
UNET DtMin=0
UNET MaxCRTS=0
UNET WFStab=0
UNET SFStab=0
UNET WFX=0
UNET SFX=0
UNET DSS MLevel=0
UNET DZMax Abort=0
UNET Convert EG Bridges=0
UNET Use Existing IB Tables=0
UNET Froude Limit=0
UNET Froude Power=0
Write IC File=0
Echo Input=False
Echo Output=False
Write Detailed=0

--- MDDLFR.f01 (steady flow) ---

Flow Title=NFF Regression Equation
Program Version=4.10
Number of Profiles= 1
Profile Names=P100yr
River Rch & RM=MDDLFR,Main            ,35609.1
 3061.72
River Rch & RM=MDDLFR,Main            ,31528.7
3107.588
River Rch & RM=MDDLFR,Main            ,31103.4
3600.187
River Rch & RM=MDDLFR,Main            ,21925.7
3811.696
River Rch & RM=MDDLFR,Main            ,20424.3
3900.349
River Rch & RM=MDDLFR,Main            ,10692.2
4118.001
River Rch & RM=MDDLFR,Main            ,9662.3
4399.793
River Rch & RM=MDDLFR,Main            ,5768.1
4537.045
River Rch & RM=MDDLFR,Main            ,133.3
4641.798
Boundary for River Rch & Prof#=MDDLFR,Main            , 1
Up Type= 0
Dn Type= 3
Dn Slope=0.00157
DSS Import GetInterval= 0
DSS Import GetPeak= 0
DSS Import FillOption= 0

--- MDDLFR.g01 (geometry) ---

Geom Title=USGS 10m DEM
Program Version=4.10

River Reach=MDDLFR          ,Main
Reach XY= 30
     1588759.285      241411.662     1587784.162      240705.836
     1587673.853       239949.72     1588924.879      238105.652
     1588433.821      237900.957     1587762.659       238869.02
     1587102.322      239082.976      1586716.06       238687.75
      1586640.76      237530.972     1585867.334      237207.636
     1584990.699      237734.066     1584143.703      239882.141
     1583197.135      240064.307     1583371.629      239652.168
     1582003.906      238792.022     1581186.216      239896.768
     1580337.155      240104.976     1580611.912      240950.203
     1579637.044      240865.958     1578846.021      241238.207
     1578272.436      240555.061     1577661.285      242287.622
     1576887.134      241278.689     1573613.857      239554.486
     1572188.876      239520.251     1572254.594      238873.576
      1571890.01      238614.244     1571096.643      239214.197
     1571319.515       240372.79     1571043.474      240787.721

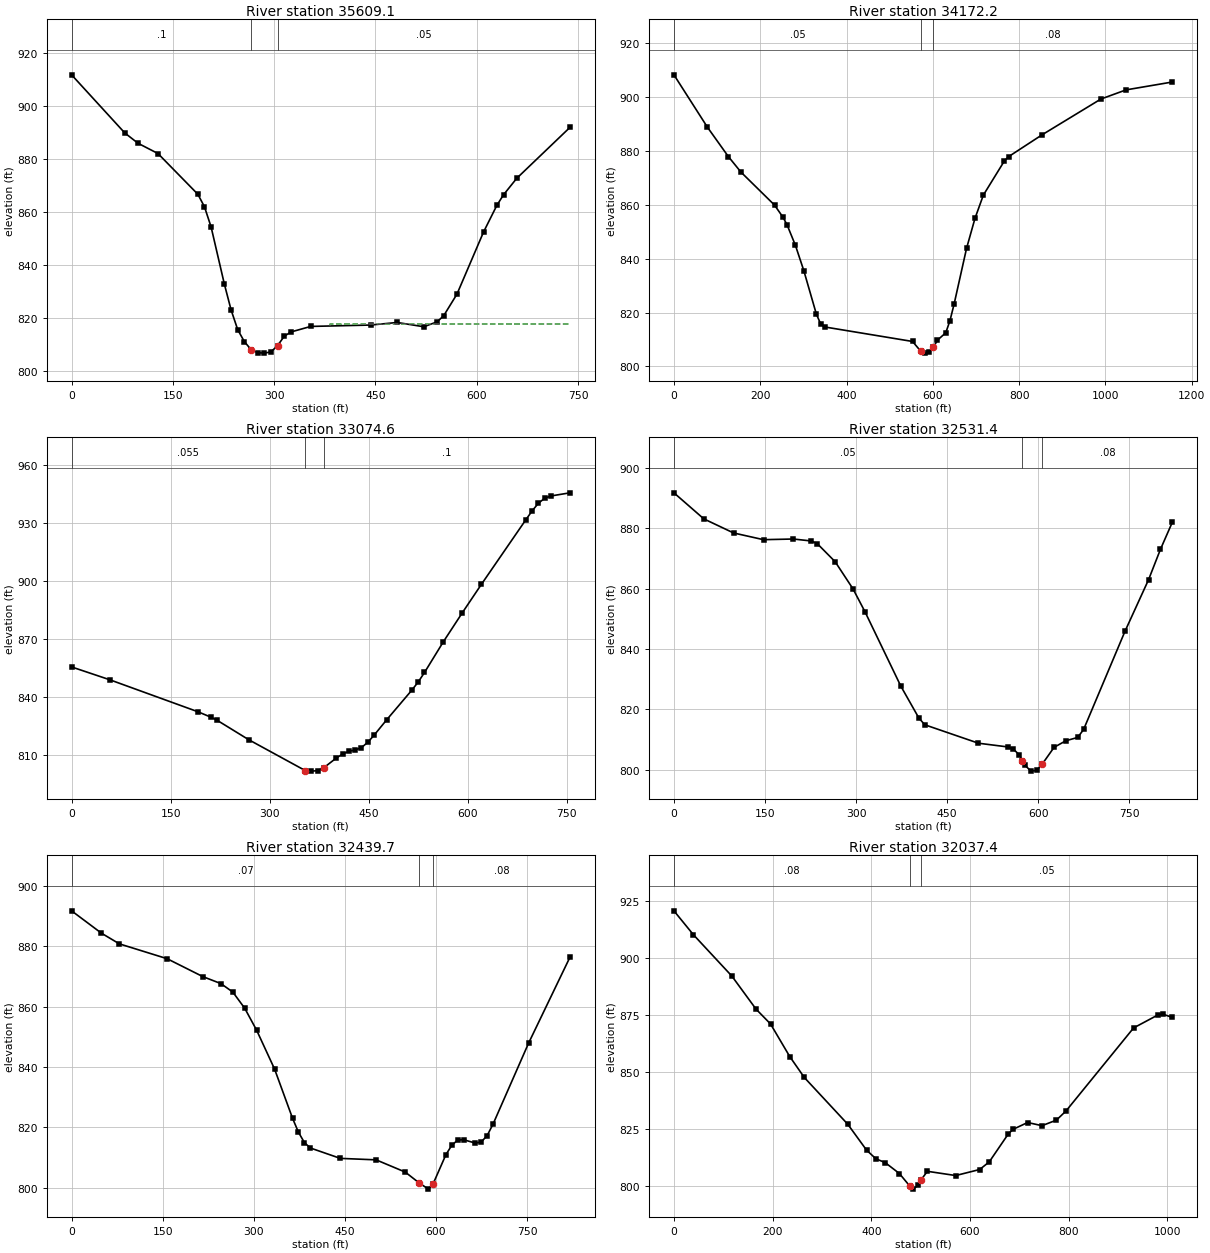
Type RM Length L Ch R = 1 ,35609.1 ,1421.8,1437,1452.1
XS GIS Cut Line= 3
     1588872.564       241147.16     1588742.355      241401.067
     1588555.723      241813.393
#Sta/Elev= 30
       0  911.67    78.7  889.75    98.4  885.83   127.9  881.96     187  866.58
   196.8  861.83   206.6  854.23   226.3  832.59   236.2  822.91     246  815.46
   255.8  810.97   265.7  807.96   275.5   806.8   285.4  806.61   295.2  807.07
     305  809.45   314.9  812.98   324.7  814.59   354.2  816.69   442.8  817.21
   482.1  818.18   521.5  816.57   541.2  818.41     551  820.73   570.7  828.91
     610  852.33   629.7  862.38   639.6  866.39   659.2  872.61   737.9  891.81
#Mann= 3 , 0 , 0
       0      .1       0   265.7    .045       0     305     .05       0
#XS Ineff= 2 , 0
                          382.92          817.63
Permanent Ineff=
       F       F
Bank Sta=265.7,305
XS Rating Curve= 0 ,0
Exp/Cntr=0.3,0.1

Type RM Length L Ch R = 1 ,34172.2 ,1072.7,1097.6,1118.2
XS GIS Cut Line= 4
     1588273.605      240314.478     1587808.327      240453.367
     1587634.716        240536.7       1587311.8      240887.395
#Sta/Elev= 30
       0  908.25    77.7  888.78   126.2  877.89   155.4  872.12   233.1  859.89
   252.5  855.44   262.2  852.55   281.6  844.92     301  835.55   330.2  819.35
   339.9  815.83   349.6  814.63     553  809.25   572.2   805.6   581.8  804.92
   591.5  805.28   601.1  807.01   610.7  809.72     630  812.49   639.6  816.92
   649.2  823.05   678.1  843.78   697.6  854.91   717.1  863.59   765.7  876.24
   775.4  877.85   853.3  885.99   989.5  899.26  1047.8  902.66  1154.9  905.58
#Mann= 3 , 0 , 0
       0     .05       0   572.2    .045       0   601.1     .08       0
Bank Sta=572.2,601.1
XS Rating Curve= 0 ,0
Exp/Cntr=0.3,0.1

Type RM Length L Ch R = 1 ,33074.6 ,533.6,543.2,552.7
XS GIS Cut Line= 4
     1588176.383       239692.95     1587922.911      239557.534
     1587756.244      239467.256     1587485.584      239405.016
#Sta/Elev= 30
       0  855.51    57.5  848.92   191.6   832.3   210.7  829.57   220.3  827.94
   268.2  817.89   353.7  801.95   363.2  801.63   372.7  801.86   382.2  803.46
   401.1  808.47   410.6   810.5   420.1  811.91   429.5  812.57     439  813.83
   448.5  816.52     458  820.18   476.9  828.08   515.2  843.49   524.8   847.7
   534.4  852.64   563.1  868.61   591.8   883.6   620.6  898.25   687.6   931.5
   697.2  936.14   706.8  940.16   716.3  942.73   725.9  943.94   754.6  945.56
#Mann= 3 , 0 , 0
       0    .055       0   353.7    .045       0   382.2      .1       0
Bank Sta=353.7,382.2
XS Rating Curve= 0 ,0
Exp/Cntr=0.3,0.1

Type RM Length L Ch R = 1 ,32531.4 ,91.7,91.7,91.7
XS GIS Cut Line= 4
     1588751.209      239389.391     1588285.064      239204.495
     1588209.543      239105.537     1588032.459      239024.808
#Sta/Elev= 30
       0  891.78    49.2  883.15    98.3  878.47   147.5  876.25   196.7  876.47
   226.2  875.82     236  874.94   265.5  868.94     295   859.9   314.6  852.36
   373.6  827.71   403.2  817.18     413   814.9   501.5  808.78   549.4  807.56
   558.9  806.83   568.5  804.97  573.85803.0417   578.1  801.51   587.7  799.53
   597.2  799.76   606.8  801.95     626  807.42   645.4   809.6   664.9   810.7
   674.6  813.33   742.7  845.86   781.6     863   801.1  873.03   820.6  881.99
#Mann= 3 , 0 , 0
       0     .05       0  573.85    .045       0   606.8     .08       0
Bank Sta=573.85,606.8
XS Rating Curve= 0 ,0
Exp/Cntr=0.3,0.1

Type RM Length L Ch R = 1 ,32439.7 ,412.3,402.4,392.3
XS GIS Cut Line= 4
     1588816.314      239324.287     1588350.168      239139.391
     1588274.647      239040.433     1588097.564      238959.704
#Sta/Elev= 30
       0  891.83    49.2  884.41    78.7  880.87   157.3  875.95   216.3  869.99
   245.8   867.7   265.5  864.88   285.2  859.48   304.8  852.19   334.3  839.32
   363.8  823.04   373.6  818.38   383.5  814.91   393.3  813.15   442.5  809.71
   501.5  809.22   549.4  805.17  572.76801.5013   587.7  799.51   595.3  801.25
   616.4  810.94     626  814.03   635.7  815.77   645.4  815.91   664.9  814.78
   674.6  815.16   684.3  817.27   694.1  821.11   752.5  847.92   820.6  876.42
#Mann= 3 , 0 , 0
       0     .07       0  572.76    .045       0   595.3     .08       0
Bank Sta=572.76,595.3
XS Rating Curve= 0 ,0
Exp/Cntr=0.3,0.1

Type RM Length L Ch R = 1 ,32037.4 ,517,508.6,499.8
XS GIS Cut Line= 5
     1589047.911      239137.395     1588742.355       238942.95
     1588575.689      238852.672     1588349.994      238793.645
     1588138.189      238870.034
#Sta/Elev= 30
       0  920.67    39.2  910.27   117.5  892.06   166.4  877.61   195.8  871.11
   234.9  856.78   264.3  847.65   352.4  827.16   390.6  815.79   409.6     812
   428.5  810.32     457  805.57   478.8  799.89   485.4  798.73   494.9   800.5
  500.63802.6945   513.8  806.54   571.2  804.68   619.8  807.33   639.2  810.67
   678.1     823   687.8  824.96     717  827.92   746.1  826.53   775.3  828.96
   794.8  832.97   931.8  869.36   980.8  875.01   990.6  875.44  1010.2  873.97
#Mann= 3 , 0 , 0
       0     .08       0   478.8    .045       0  500.63     .05       0
Bank Sta=478.8,500.63
XS Rating Curve= 0 ,0
Exp/Cntr=0.3,0.1

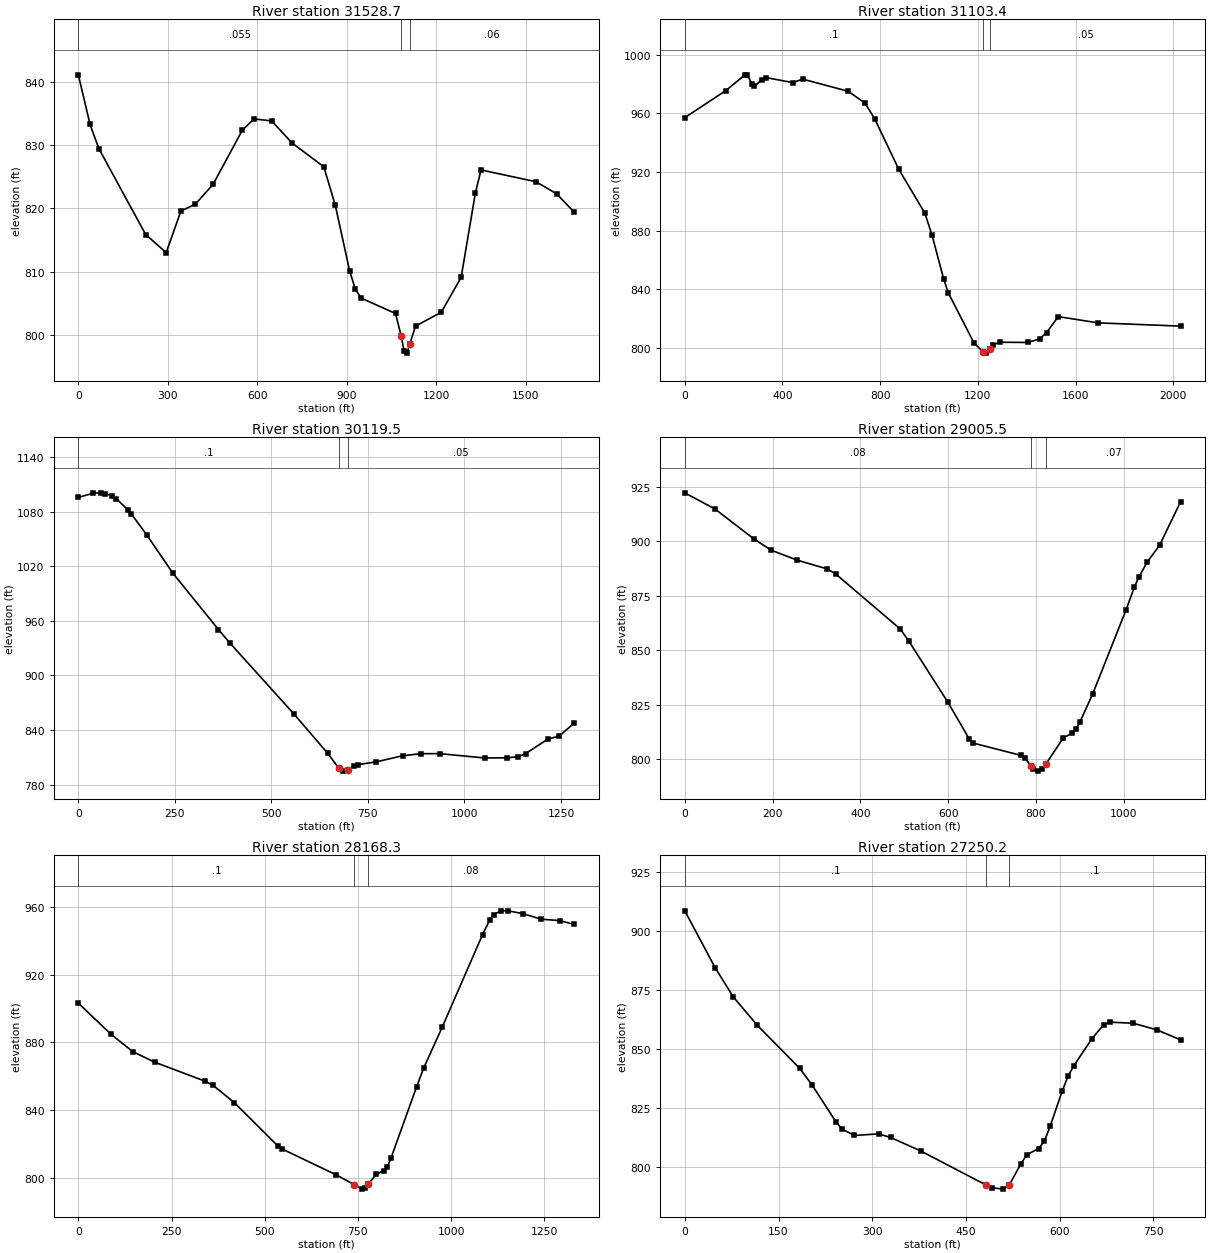
Type RM Length L Ch R = 1 ,31528.7 ,437.8,425.3,411.5
XS GIS Cut Line= 6
     1589992.355      238498.506     1589256.244       238505.45
      1588968.05      238491.561     1588787.494      238467.256
     1588568.744      238467.256     1588346.522      238547.117
#Sta/Elev= 30
       0  841.07    39.3  833.24    68.7  829.44   225.8  815.88   294.5  813.03
   343.5  819.56   392.6   820.7   451.5  823.79   549.6  832.34   588.9  834.11
   647.8  833.81   716.5  830.31   822.7  826.57   861.2  820.48   909.3  810.13
   928.5  807.24   947.7  805.86    1063  803.43  1082.2  799.85  1091.8  797.52
  1101.4  797.18    1111  798.68  1130.2  801.44  1216.4  803.63  1282.9  809.12
  1330.5  822.39  1349.5  826.07  1533.8  824.21  1602.7  822.31  1661.7  819.42
#Mann= 3 , 0 , 0
       0    .055       0  1082.2    .045       0    1111     .06       0
Bank Sta=1082.2,1111
XS Rating Curve= 0 ,0
Exp/Cntr=0.3,0.1

Type RM Length L Ch R = 1 ,31103.4 ,1016,983.9,951.5
XS GIS Cut Line= 5
     1590054.855      237626.978     1589176.383      237946.422
     1588846.522      238123.506     1588568.744      238251.978
     1588273.605      238543.645
#Sta/Elev= 30
       0  957.14   167.3  975.47     246  986.25   255.8  986.32   275.5  979.78
   285.3  978.41   314.9  983.13   334.5  984.38   442.8  980.98   482.1  983.41
   669.1  975.08     738  967.02   777.3  956.36   875.7  922.01   982.8     892
  1011.6  877.33  1059.6  847.24  1078.8  837.61  1184.3  803.32  1222.7  797.09
  1232.3  796.44  1251.5  799.55  1261.1  802.03  1289.9  803.87  1404.8  803.72
  1452.6  806.15  1481.3  810.45  1529.1  821.35  1692.4  817.08  2030.1  814.87
#Mann= 3 , 0 , 0
       0      .1       0  1222.7    .045       0  1251.5     .05       0
Bank Sta=1222.7,1251.5
XS Rating Curve= 0 ,0
Exp/Cntr=0.3,0.1

Type RM Length L Ch R = 1 ,30119.5 ,1110.8,1114,1116
XS GIS Cut Line= 4
     1587881.244      237467.256     1588034.022      237995.034
     1588120.827      238220.728     1588175.689      238710.572
#Sta/Elev= 30
       0 1095.57    39.2 1100.23    58.9 1100.59    68.7 1099.85    88.3 1096.99
    98.1 1094.16   127.6 1082.24   137.4 1077.38   176.6  1054.7   245.3 1012.06
     363  950.35   392.5  935.62   559.1  857.33   646.2  814.27   675.2  797.79
   684.9  794.87  699.03796.5741   713.9  800.44   723.6     802   771.9  805.02
   839.6  811.79   887.9  814.03   936.2  814.08  1052.2  809.32  1110.2  809.48
  1139.2   810.7  1158.5  814.13  1216.5  830.16  1245.5  833.35  1284.2  847.58
#Mann= 3 , 0 , 0
       0      .1       0   675.2    .045       0  699.03     .05       0
Bank Sta=675.2,699.03
XS Rating Curve= 0 ,0
Exp/Cntr=0.3,0.1

Type RM Length L Ch R = 1 ,29005.5 ,815.8,837.2,858.7
XS GIS Cut Line= 4
       1587374.3      238236.353     1587474.126      238826.631
      1587530.55      239074.027     1587595.654      239343.124
#Sta/Elev= 30
       0  922.15    68.7  914.75     157  901.09   196.3   895.9   255.2  891.35
   323.9   887.3   343.5  885.01   490.7  859.76   510.3  854.19   598.7  826.35
   647.5   809.5   657.2  807.45   764.6  801.89   774.3  800.73  788.39797.0313
   793.8  795.57   803.6  794.62   813.4   795.5   823.1  798.08     862  809.82
     881  811.91   890.6   813.7   900.1  817.23   928.8  829.88  1005.2  868.61
  1024.2  879.09  1033.8  883.35  1052.9  890.33  1081.5  898.17  1129.3  918.11
#Mann= 3 , 0 , 0
       0     .08       0  788.39    .045       0   823.1     .07       0
Bank Sta=788.39,823.1
XS Rating Curve= 0 ,0
Exp/Cntr=0.3,0.1

Type RM Length L Ch R = 1 ,28168.3 ,904.8,918.2,932.2
XS GIS Cut Line= 4
     1587283.154      238253.714     1586953.293      238687.742
     1586736.279      238926.457     1586475.862      239308.402
#Sta/Elev= 30
       0  903.08    87.6  884.69     146  874.43   204.4  868.23   340.7  856.89
   360.2  854.73   418.6  844.26   535.4  818.64   545.2  817.05   691.8   801.6
   740.7  795.76   760.2  793.17   769.9  794.08  777.16 796.016   799.3  801.93
   818.9  804.14   828.7  806.22   838.4   811.3   907.1  853.48   926.8  864.96
     976  888.84  1084.2  943.55  1103.8  952.35  1113.7  955.37  1133.3  957.63
    1153  957.64  1192.3  955.97  1241.5  952.69  1290.7  951.88    1330  949.63
#Mann= 3 , 0 , 0
       0      .1       0   740.7    .045       0  777.16     .08       0
Bank Sta=740.7,777.16
XS Rating Curve= 0 ,0
Exp/Cntr=0.3,0.1

Type RM Length L Ch R = 1 ,27250.2 ,231,226.8,221.8
XS GIS Cut Line= 4
     1587157.286      237858.749      1586757.98      237936.874
     1586584.369      237975.936     1586384.716        238036.7
#Sta/Elev= 30
       0  908.71    48.4  884.68    77.5  872.25   116.2  860.15   184.1  841.88
   203.4     835   242.2  819.16   251.9  816.17   271.2   813.5     310  814.16
   329.4  812.65   377.8   806.9   481.8  792.53   491.2  791.35   509.9  790.75
   519.5  792.61     538  801.52   547.4  805.32   566.1  807.95   575.5  811.11
   584.8  817.45   603.8  832.23   613.3  838.59   622.8  843.14   651.2  854.38
   670.2   860.4   679.7  861.53   717.6  861.06   755.6  858.26   793.5  854.01
#Mann= 3 , 0 , 0
       0      .1       0   481.8    .045       0   519.5      .1       0
Bank Sta=481.8,519.5
XS Rating Curve= 0 ,0
Exp/Cntr=0.3,0.1

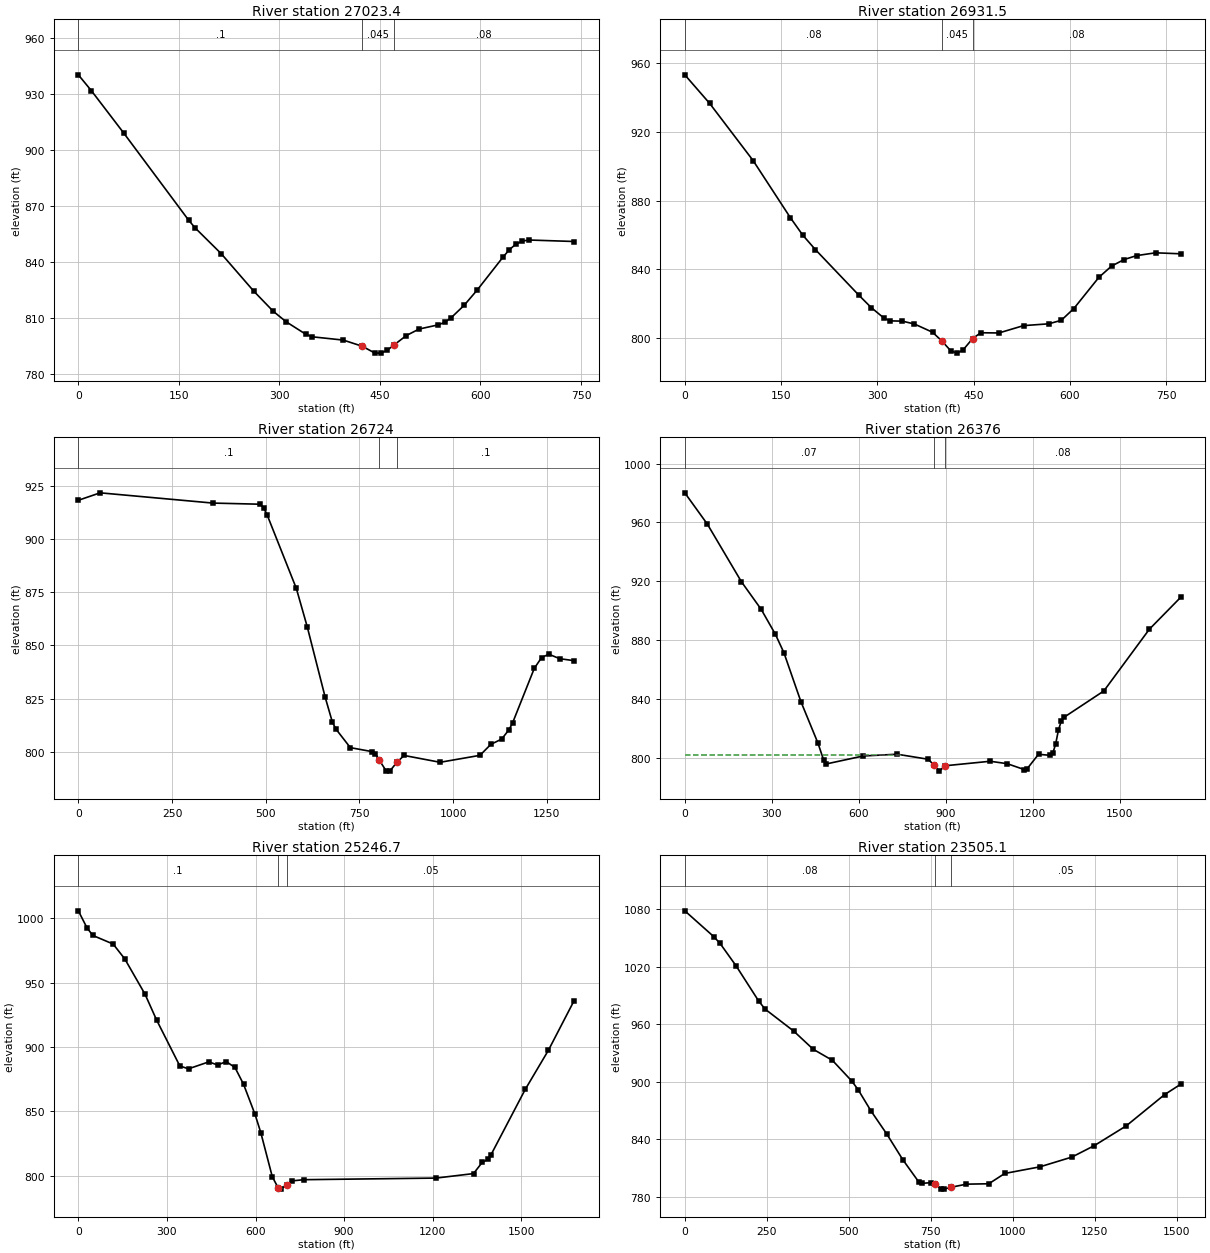
Type RM Length L Ch R = 1 ,27023.4 ,91.9,91.9,91.9
XS GIS Cut Line= 4
     1587100.862      237611.353     1586771.001      237689.478
     1586614.751      237754.582     1586415.098       237871.77
#Sta/Elev= 30
       0  940.17    19.4  931.72    67.8  909.02   164.6  862.45   174.3  858.32
   213.1  844.58   261.5  824.61   290.6  813.82   309.9  808.18     339  801.55
   348.4  800.13   395.4  798.35   423.6  795.06   442.4  791.42   451.8  791.38
   461.2  792.98   470.6  795.62   489.4  800.78   508.3  804.24   537.2  806.51
   546.8  807.87   556.5  810.38   575.8     817   595.1   825.1   633.7  842.74
   643.3  846.75     653  849.68   662.6  851.29   672.2  851.86   739.8  851.06
#Mann= 3 , 0 , 0
       0      .1       0   423.6    .045       0   470.6     .08       0
Bank Sta=423.6,470.6
XS Rating Curve= 0 ,0
Exp/Cntr=0.3,0.1

Type RM Length L Ch R = 1 ,26931.5 ,217.8,207.5,197.2
XS GIS Cut Line= 4
     1587079.161      237531.058       1586749.3      237609.183
      1586593.05      237674.287     1586395.567      237850.068
#Sta/Elev= 30
       0  953.19    38.7  936.58   106.5  903.28   164.6  870.02     184  859.83
   203.4  851.55   271.2  824.99   290.6  817.75   309.9   811.8   319.6  810.05
     339  809.89   357.8  808.22     386  803.44  400.91798.2267   414.2  792.73
   423.6  791.28     433  792.87  448.56799.7813   461.2  803.13   489.4  803.01
   527.8  807.28     567  808.33   586.6  810.37   606.2  817.21   645.3  835.39
   664.9  841.91   684.5  845.72   704.1  848.02   733.5  849.64   772.6  849.07
#Mann= 3 , 0 , 0
       0     .08       0  400.91    .045       0  448.56     .08       0
Bank Sta=400.91,448.56
XS Rating Curve= 0 ,0
Exp/Cntr=0.3,0.1

Type RM Length L Ch R = 1 ,26724   ,357.9,348,337.7
XS GIS Cut Line= 4
     1587170.307      236895.207     1586701.557      237316.214
     1586519.265      237537.568     1586349.994      237906.492
#Sta/Elev= 30
       0  918.14    58.2  921.64   358.6  916.83   484.7  916.29   494.4  914.58
     504  911.12   581.6  876.73   610.7   858.7   658.7  825.54   677.8  813.91
   687.4  810.66   725.6  801.99     783  800.14   792.6  799.17   802.1  796.35
   821.2  791.05   830.8  790.96   849.9  795.12     869  798.32   965.1  795.11
  1071.4  798.37  1100.4  803.52  1129.4  806.02  1148.8  810.39  1158.4  813.59
  1216.4  839.24  1235.7  844.25  1255.1  845.86  1284.1  843.76  1322.7  842.82
#Mann= 3 , 0 , 0
       0      .1       0   802.1    .045       0   849.9      .1       0
Bank Sta=802.1,849.9
XS Rating Curve= 0 ,0
Exp/Cntr=0.3,0.1

Type RM Length L Ch R = 1 ,26376   ,1147.5,1129.3,1110.6
XS GIS Cut Line= 4
     1586467.182      236576.197     1586263.189      237309.704
     1586206.765      237535.398      1585976.73      238212.481
#Sta/Elev= 30
       0  980.09    78.1  958.73   195.2  919.71   263.5  900.92   312.4  883.99
   341.6  871.56   400.2  838.32   458.8  810.25   478.3  798.83     488  796.02
   614.9  801.42   732.1   802.6   838.9   799.2   858.3  795.39   877.7  791.13
     897  794.77  1052.8  797.83  1111.5  796.17  1170.3  792.18  1180.1  792.76
  1219.3  802.56  1258.5  801.87  1268.3  803.26  1278.1  809.34  1287.9  818.98
  1297.6  825.03  1307.4  827.72  1444.6  845.59  1601.3  887.47  1709.1   909.1
#Mann= 3 , 0 , 0
       0     .07       0   858.3    .045       0     897     .08       0
#XS Ineff= 2 , 0
          756.11  802.35
Permanent Ineff=
       F       F
Bank Sta=858.3,897
XS Rating Curve= 0 ,0
Exp/Cntr=0.3,0.1

Type RM Length L Ch R = 1 ,25246.7 ,1762.5,1741.6,1719.9
XS GIS Cut Line= 4
     1584909.022      236875.676     1585225.862      237301.023
     1585438.536      237661.266     1585742.355      238325.329
#Sta/Elev= 30
       0 1005.72    29.5  992.43    49.1   986.6   117.9  979.91   157.2  968.39
   225.9  940.92   265.2  920.81   343.8  885.15   373.2  882.99     442  888.39
   471.4  885.95   500.9  888.57   530.4  884.04   559.6  870.91   598.5  847.49
   617.9  833.39   656.9  799.05   676.3  790.69     686  789.51   705.5  792.94
     725  795.95   763.9  796.84  1211.6   798.1  1338.2  801.58  1367.4  810.22
  1386.9  812.59  1396.6  815.84  1513.5  867.04  1591.4  897.22    1679     936
#Mann= 3 , 0 , 0
       0      .1       0   676.3    .045       0   705.5     .05       0
Bank Sta=676.3,705.5
XS Rating Curve= 0 ,0
Exp/Cntr=0.3,0.1

Type RM Length L Ch R = 1 ,23505.1 ,1559.6,1579.4,1597.4
XS GIS Cut Line= 4
     1583702.425      238724.634      1584253.64      238859.183
     1584592.182      238889.565       1585186.8      238998.072
#Sta/Elev= 30
       0 1078.11      88  1051.3   107.6  1044.1   156.5 1020.68     225  984.22
   244.6  975.71   332.6  952.57   391.3  933.84     450  922.26   508.7  900.81
   528.3  891.74   567.4  869.64     616  845.33   664.5  818.75   713.1  795.59
   722.8  794.03   751.9  794.74   761.6  793.39     781  788.52   790.8  787.99
   810.2  789.83   858.7  793.17   926.8  793.58   975.5  804.33  1082.8  811.24
  1180.3  821.42  1248.5  833.33    1346  853.97    1463  886.58  1511.7  897.26
#Mann= 3 , 0 , 0
       0     .08       0   761.6    .045       0   810.2     .05       0
Bank Sta=761.6,810.2
XS Rating Curve= 0 ,0
Exp/Cntr=0.3,0.1

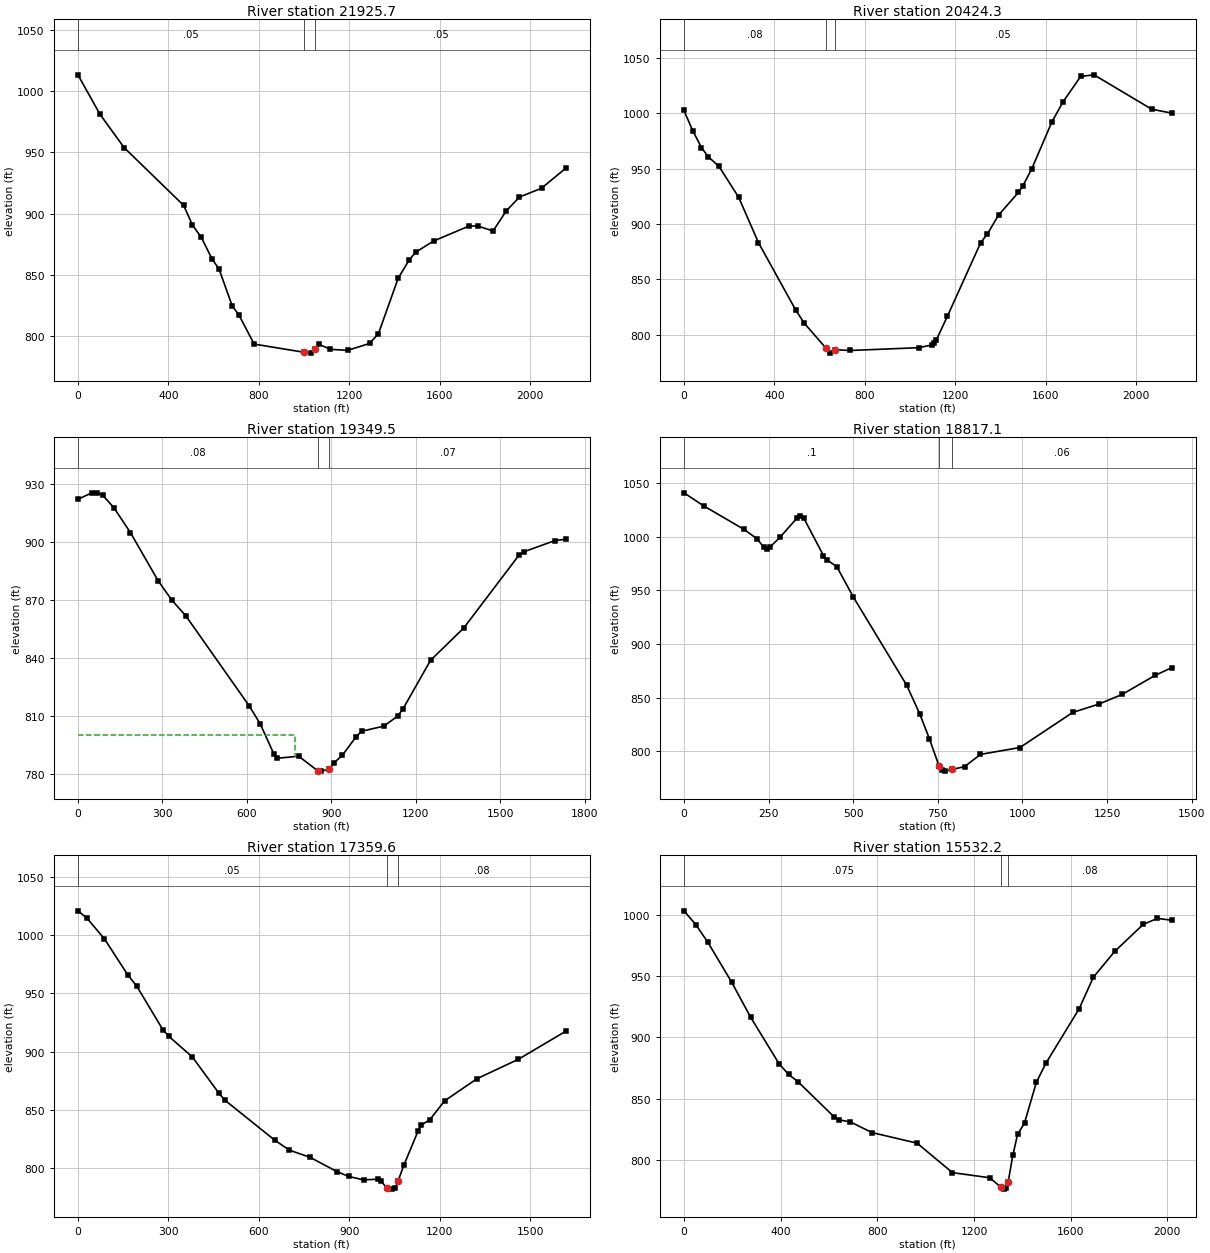
Type RM Length L Ch R = 1 ,21925.7 ,1471.6,1501.4,1529.8
XS GIS Cut Line= 4
     1583560.064      238968.558     1583815.272      239827.933
     1583987.147        240057.1     1584721.522      240697.725
#Sta/Elev= 30
       0 1013.24    97.4  981.03   204.6  953.76   467.7  906.59   506.7  890.52
   545.7   880.5   594.4  862.45   623.6   854.9   682.1  824.67   711.3  817.36
   779.5  793.38  1001.5  786.65  1030.2     786  1049.2  789.57  1068.3  793.06
  1116.1  789.11  1192.7  788.24  1290.1  793.91  1329.1   801.9  1416.8  847.35
  1465.5  862.18  1494.8  868.54  1572.7  877.51  1728.7   889.7  1767.6  889.91
  1835.9   885.7  1894.3  902.09  1952.8  913.44  2050.3  920.64  2157.5  936.98
#Mann= 3 , 0 , 0
       0     .05       0  1001.5    .045       0  1049.2     .05       0
Bank Sta=1001.5,1049.2
XS Rating Curve= 0 ,0
Exp/Cntr=0.3,0.1

Type RM Length L Ch R = 1 ,20424.3 ,1074.3,1074.8,1075.1
XS GIS Cut Line= 4
      1583507.98       238963.35     1583336.105      239353.975
     1583138.189      239661.266     1582481.939      240859.183
#Sta/Elev= 30
       0 1002.34    38.8  984.12    77.6  968.92   106.7  960.78   155.2  951.84
   242.5  923.91   329.8  883.09   494.1  822.54   532.6  810.45   628.8  787.91
     648  783.52   667.2   786.6   734.6   785.9  1037.9  788.41  1096.9  790.84
  1106.7  792.51  1116.6  795.31  1165.7  816.83  1313.1  883.19  1342.6  890.98
  1391.7  907.92  1480.1  928.51  1499.8  934.52  1539.1   949.8  1627.5  991.83
  1676.7 1009.97  1755.3 1033.03  1814.2 1034.48  2069.7 1003.45  2158.2  999.96
#Mann= 3 , 0 , 0
       0     .08       0   628.8    .045       0   667.2     .05       0
Bank Sta=628.8,667.2
XS Rating Curve= 0 ,0
Exp/Cntr=0.3,0.1

Type RM Length L Ch R = 1 ,19349.5 ,555.1,532.5,509.9
XS GIS Cut Line= 4
     1582977.946      238201.718     1582639.404      238597.551
     1582358.154      238982.968     1582128.987      239680.884
#Sta/Elev= 30
       0  922.03    49.1  925.39    68.8  925.35    88.4   924.1   127.8  917.66
   186.7  904.76     285  879.86   334.1  869.75   383.3  861.73   608.5  815.11
   647.4  805.87   696.1  790.22   705.9  788.01   783.8  789.14   851.9  781.57
   861.7   781.4  892.38782.2966   910.4  785.83   939.6  789.64   988.2  799.25
  1007.8  802.03  1086.1  804.67  1135.1   809.8  1154.7  813.65  1252.6  838.78
  1370.2  855.43  1566.1  893.06  1585.6  894.97  1693.4  900.66  1732.6  901.36
#Mann= 3 , 0 , 0
       0     .08       0   851.9    .045       0  892.38     .07       0
#XS Ineff= 2 , 0
          770.57     800
Permanent Ineff=
       F       F
Bank Sta=851.9,892.38
XS Rating Curve= 0 ,0
Exp/Cntr=0.3,0.1

Type RM Length L Ch R = 1 ,18817.1 ,1468.4,1457.4,1446.7
XS GIS Cut Line= 4
     1581634.196      238123.593     1581951.904      238732.968
     1582030.029      238915.259     1582092.529      239467.343
#Sta/Elev= 30
       0 1040.77    58.9  1028.5   176.7 1006.86     216  998.01   235.6  990.09
   245.4  988.93   255.2  990.56   284.7  999.66   333.8 1017.19   343.6 1019.04
   353.4 1017.63   412.3  982.33   422.2  978.39   451.6  972.03   500.7  943.64
   657.8   861.8   696.7  834.95     725  811.91   753.3  786.84   762.8  782.42
   772.2  781.67   791.1   783.2   828.9  785.82   876.1  797.24   992.8  803.66
  1148.7  836.32  1226.7  844.18    1295  853.15  1392.4  870.88  1441.2     878
#Mann= 3 , 0 , 0
       0      .1       0   753.3    .045       0   791.1     .06       0
Bank Sta=753.3,791.1
XS Rating Curve= 0 ,0
Exp/Cntr=0.3,0.1

Type RM Length L Ch R = 1 ,17359.6 ,1827.4,1827.4,1826.3
XS GIS Cut Line= 5
     1580444.959      239134.009     1580908.501      239660.051
     1581038.709      239868.384     1581189.751      240014.218
     1581507.459      240347.551
#Sta/Elev= 30
       0 1021.16    29.2 1015.01    87.6   997.1   165.6  965.88   194.8  956.37
   282.4  918.45   301.9  912.98   379.8  895.19   467.4  864.09   486.9  858.19
   652.4  823.69   701.1  815.12   769.9  808.89   858.4  796.67   897.7  792.44
   946.8  789.53   994.5  790.06  1004.1  788.94  1023.2   782.6  1042.2  781.54
  1051.8  782.69  1061.3  788.51  1080.4  802.02  1128.1  831.83  1137.7  836.57
  1166.6  841.26  1215.6  857.55  1323.3  876.66  1460.5  893.36  1617.3  917.47
#Mann= 3 , 0 , 0
       0     .05       0  1023.2    .045       0  1061.3     .08       0
Bank Sta=1023.2,1061.3
XS Rating Curve= 0 ,0
Exp/Cntr=0.3,0.1

Type RM Length L Ch R = 1 ,15532.2 ,1954.7,1978.5,2000.9
XS GIS Cut Line= 4
     1579606.418      240107.968     1580450.168      240738.176
     1580747.043      240967.343     1581033.501      241482.968
#Sta/Elev= 30
       0 1003.17    49.2  991.88    98.4   977.7   196.8  945.16   275.6  916.49
   393.7  878.36   433.1  869.71   472.4  863.69   620.1  835.32   639.8  832.71
     689  830.96   777.5  822.32   964.6  813.66  1110.8  789.62  1264.7  785.46
  1312.8  777.53  1322.3  776.17    1332  777.07  1341.6  782.36  1360.8  804.05
  1380.1  820.74  1408.9  830.18  1457.7  863.15    1497  878.77  1634.6  923.16
  1693.6  948.98  1782.1  970.07    1900  992.15    1959  996.99    2018  995.47
#Mann= 3 , 0 , 0
       0    .075       0  1312.8    .045       0  1341.6     .08       0
Bank Sta=1312.8,1341.6
XS Rating Curve= 0 ,0
Exp/Cntr=0.3,0.1

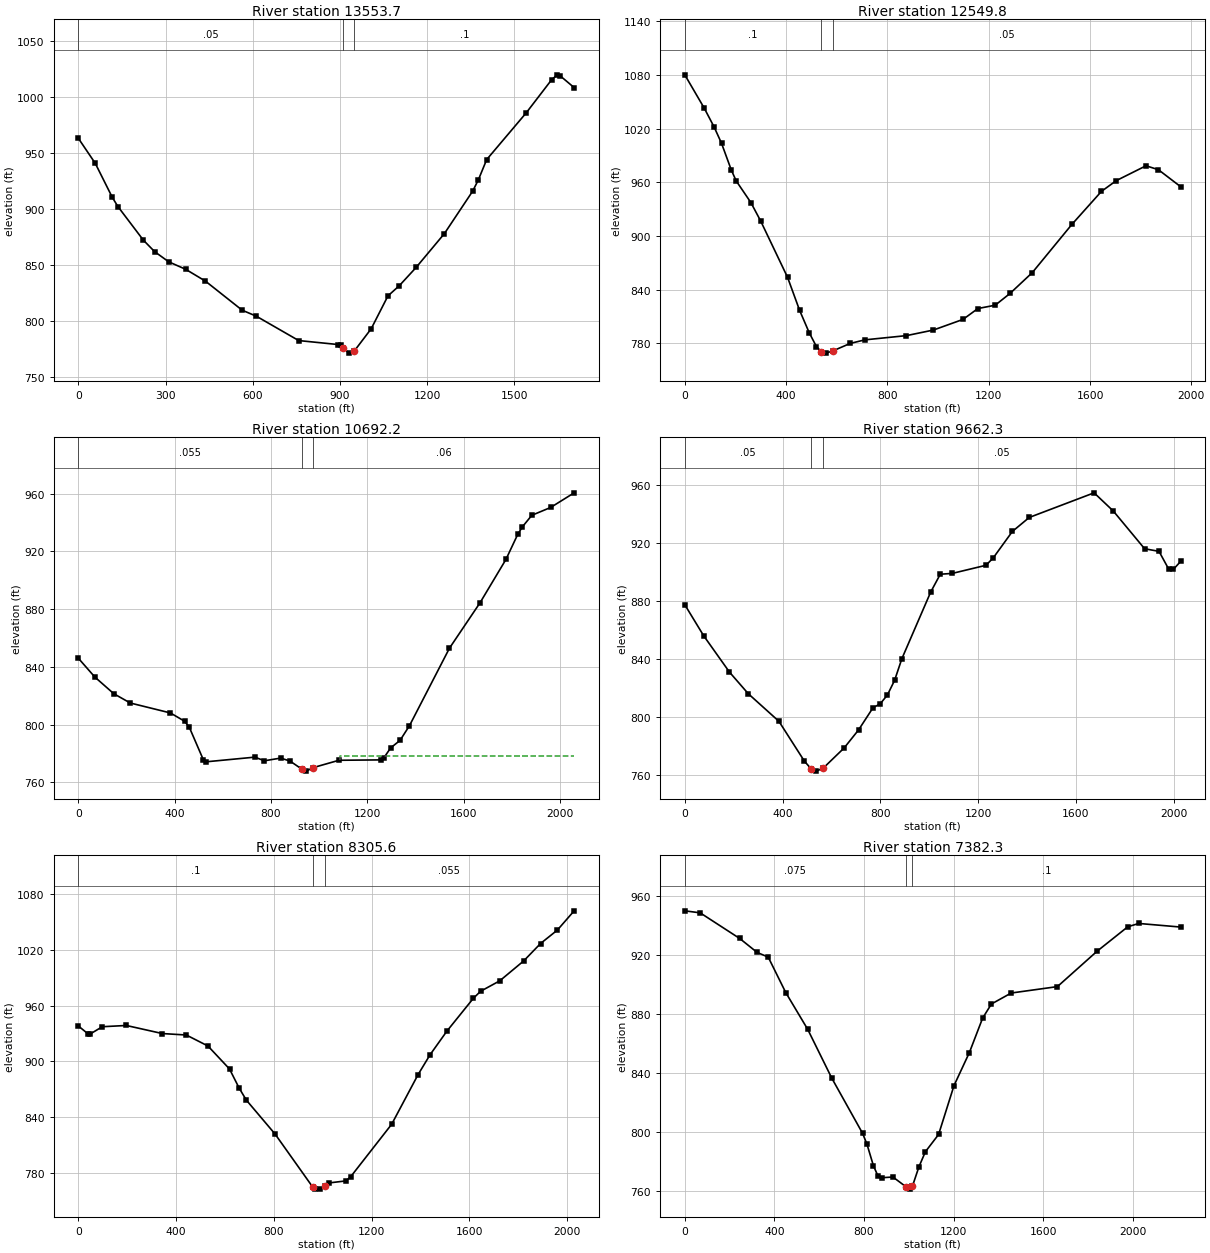
Type RM Length L Ch R = 1 ,13553.7 ,1009.6,1003.9,998.2
XS GIS Cut Line= 4
     1579064.751      240331.926     1578865.098      241073.245
     1578839.057      241359.704     1578872.043      242009.009
#Sta/Elev= 30
       0  963.22    58.3  940.82   116.6  910.57     136  902.29   223.5  872.31
   262.4     862     311   852.9   369.3  846.23   437.3  835.66   563.6   809.7
   612.2  804.38     758  782.61   892.4  779.09     902  778.48   911.6  775.79
   930.7  771.39   949.9  773.52  1007.4  793.16  1065.1  822.52  1103.9  831.55
  1162.1  847.95  1259.2  878.12  1356.2  915.93  1375.6  925.89  1404.7  944.23
  1540.6  985.91  1627.9 1015.44  1647.3 1019.86    1657 1019.04  1705.5 1008.45
#Mann= 3 , 0 , 0
       0     .05       0   911.6    .045       0   949.9      .1       0
Bank Sta=911.6,949.9
XS Rating Curve= 0 ,0
Exp/Cntr=0.3,0.1

Type RM Length L Ch R = 1 ,12549.8 ,1862.5,1857.6,1851.9
XS GIS Cut Line= 5
     1578167.182      240005.537     1578255.723       240401.37
      1578297.39      240625.329     1578339.057      241000.329
     1578531.765      241927.412
#Sta/Elev= 30
       0 1080.08    77.3 1042.55   115.9 1021.68   144.9 1003.62   183.5  973.73
   202.8  961.53   260.8  937.31   299.4  916.73   405.6  853.76   453.1   816.9
     491  791.86   519.5  776.33   538.5  770.65   557.5  768.92     586  771.59
   652.8  779.74   710.8  783.76   875.3   788.5   981.7  794.75  1098.6  806.65
  1157.2  818.79  1225.5  822.49  1284.1  835.67  1371.9  858.92  1528.1  912.78
  1645.2  949.83  1703.8  961.82    1821  978.39  1869.8  974.01  1957.6  955.02
#Mann= 3 , 0 , 0
       0      .1       0   538.5    .045       0     586     .05       0
Bank Sta=538.5,586
XS Rating Curve= 0 ,0
Exp/Cntr=0.3,0.1

Type RM Length L Ch R = 1 ,10692.2 ,997.6,1029.9,1060.2
XS GIS Cut Line= 5
     1577460.584      241352.759     1577616.834      241878.801
     1577663.709      242195.641     1577721.001       242338.87
     1578523.084      242993.384
#Sta/Elev= 30
       0  845.99    68.6  832.94     147  821.42   215.6  814.96   382.2  808.07
     441  802.34   460.6   798.2   519.4  775.46   529.2  774.18   733.2  777.44
     772   774.9   839.9  776.77   878.7  774.74   926.9  769.25   946.2  767.74
   975.1  770.17  1081.9  775.26  1257.7  775.53  1267.5  776.72  1296.8  783.85
  1335.8  789.06  1374.9  799.25  1540.9  852.96  1667.9  884.46  1775.3  914.45
  1824.2  931.79  1843.7  937.07  1882.8  945.06  1960.9  950.48  2058.6  960.63
#Mann= 3 , 0 , 0
       0    .055       0   926.9    .045       0   975.1     .06       0
#XS Ineff= 2 , 0
                         1086.87          778.24
Permanent Ineff=
       F       F
Bank Sta=926.9,975.1
XS Rating Curve= 0 ,0
Exp/Cntr=0.3,0.1

Type RM Length L Ch R = 1 ,9662.3  ,1365.2,1356.7,1348.4
XS GIS Cut Line= 4
     1577361.626      241212.134     1577171.001      241568.558
     1576984.369      241681.405     1576642.876      243045.468
#Sta/Elev= 30
       0  877.41      77  856.06   182.8  830.91   259.8  815.99     385  796.98
   489.5  769.43     518  763.96     537   762.6   565.4  764.52   651.8  778.58
   710.8  791.02   769.8  806.29   799.3  809.02   828.8  815.12   858.3  825.25
   887.8  840.08  1005.8  886.11  1045.1  898.45  1094.3  899.03    1232  904.62
  1261.5  909.66  1340.1  927.97    1409  937.62  1674.4  954.62  1753.1  942.04
    1881  916.04    1940  914.24  1979.3  902.08    1999  901.86  2028.4   907.3
#Mann= 3 , 0 , 0
       0     .05       0     518    .045       0   565.4     .05       0
Bank Sta=518,565.4
XS Rating Curve= 0 ,0
Exp/Cntr=0.3,0.1

Type RM Length L Ch R = 1 ,8305.6  ,925.8,923.3,921
XS GIS Cut Line= 4
     1576837.668      240436.613     1576103.293       240790.78
     1575967.876       240978.28     1575587.668       241884.53
#Sta/Elev= 30
       0  938.02    39.3  929.64    49.1  929.49    98.2  937.22   196.5  938.55
   343.8  929.87     442   928.3   530.4  916.51   618.8  891.77   658.2  871.24
   687.6  858.32   805.5  821.74   959.9   764.6   969.5   762.6   988.8  762.67
  1008.1  766.22  1027.3  769.31  1095.7  771.46  1115.4  776.16  1282.5  832.36
  1390.6  885.76  1439.7   907.1  1508.5  932.48  1616.6  967.68  1646.1  975.28
  1724.7  986.53    1823    1008  1891.8 1026.66  1960.6  1041.1  2029.4 1061.82
#Mann= 3 , 0 , 0
       0      .1       0   959.9    .045       0  1008.1    .055       0
Bank Sta=959.9,1008.1
XS Rating Curve= 0 ,0
Exp/Cntr=0.3,0.1

Type RM Length L Ch R = 1 ,7382.3  ,1618.7,1614.2,1607.6
XS GIS Cut Line= 4
     1576004.334       239978.28     1575285.584      240337.655
     1575150.168       240572.03     1574967.876       241697.03
#Sta/Elev= 30
       0  949.75    68.6  948.39     245  931.06   323.4  921.56   372.4  918.46
   450.8  894.45   548.8  869.57   656.6  836.46   793.8  799.22   813.2  791.97
   842.3  777.26   861.6  770.68   880.9   769.2   929.3  769.66   987.3   763.1
  1006.6  761.47  1016.3  763.39  1045.3  776.52  1074.3  786.78  1133.2  798.44
    1202  831.51  1270.8   853.9  1329.7  877.12    1369  886.71  1457.4  894.14
  1663.8  898.48  1840.6  922.39  1978.2  938.99  2027.3   941.2  2213.9  938.77
#Mann= 3 , 0 , 0
       0    .075       0   987.3    .045       0  1016.3      .1       0
Bank Sta=987.3,1016.3
XS Rating Curve= 0 ,0
Exp/Cntr=0.3,0.1

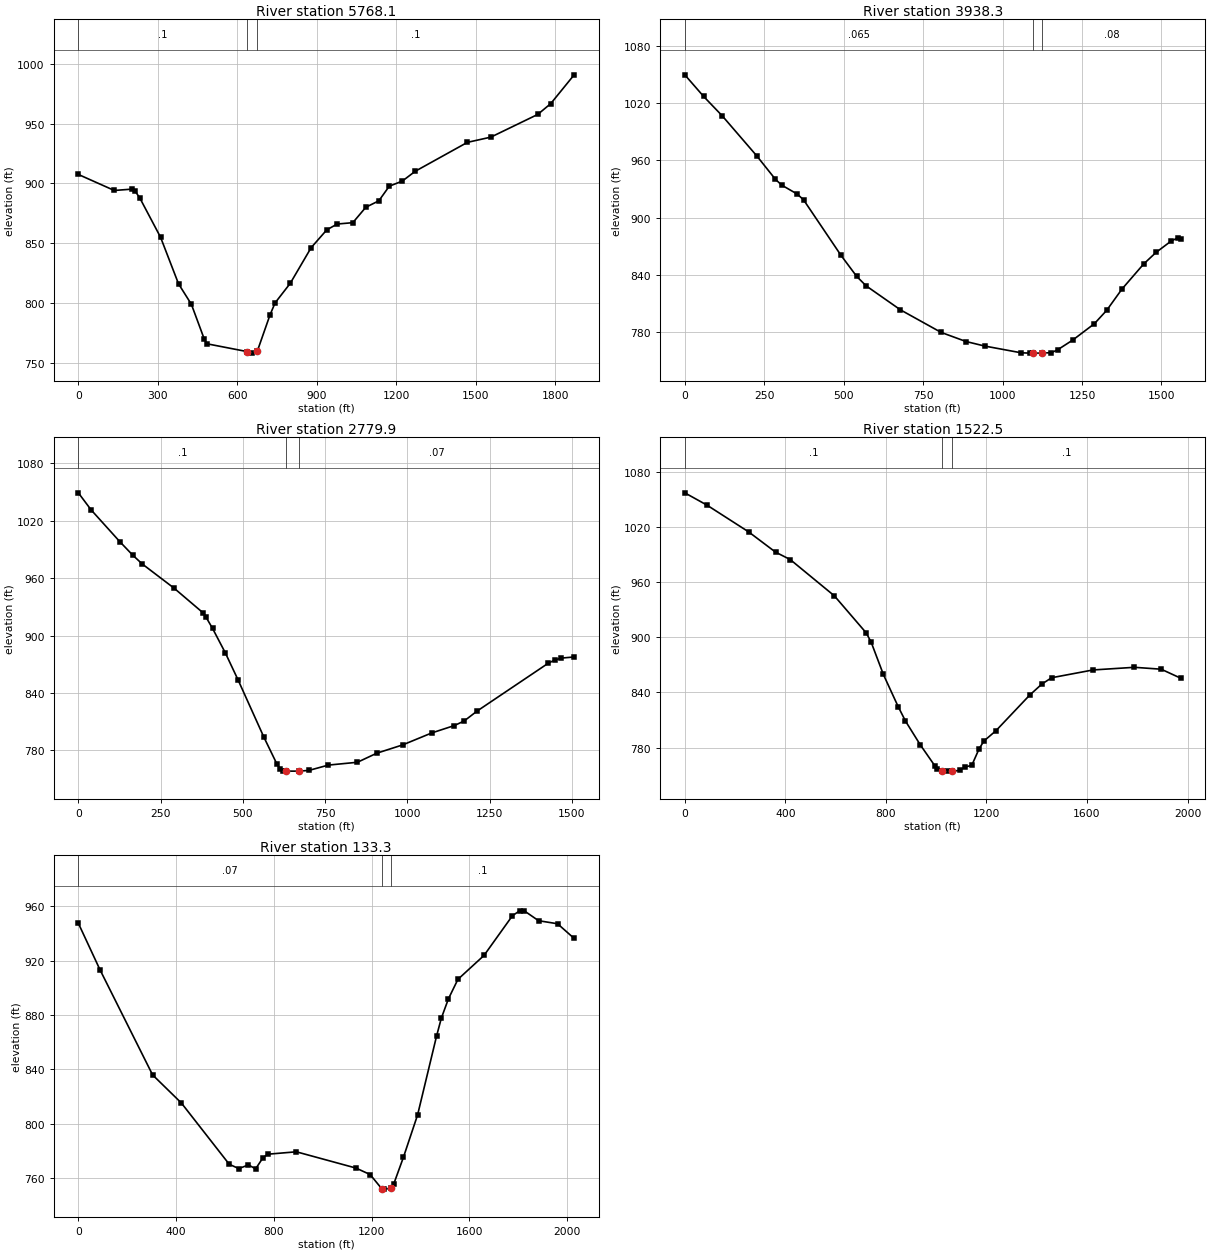
Type RM Length L Ch R = 1 ,5768.1  ,1820.3,1829.8,1838.4
XS GIS Cut Line= 4
     1573962.668      239155.363     1573874.126      239681.405
     1573796.001      239926.197     1573660.584      240999.113
#Sta/Elev= 30
       0  907.56   135.8  894.18   203.7  895.32   213.4  894.04   232.8  887.59
   310.4  855.11   378.3  816.18   426.8   799.1   475.2  770.19     485  766.15
   638.1  759.57   657.2  758.33   676.2  760.29   723.8  790.37   742.8   800.3
   800.2  816.68   878.9  846.42   937.9  861.29   977.2  866.15  1036.2  867.28
  1085.3  880.15  1134.5  885.55  1173.8  897.73    1223  902.02  1272.1  910.25
  1468.8  934.36  1557.2  938.72  1734.2  957.67  1783.4  966.71  1871.8  990.76
#Mann= 3 , 0 , 0
       0      .1       0   638.1    .045       0   676.2      .1       0
Bank Sta=638.1,676.2
XS Rating Curve= 0 ,0
Exp/Cntr=0.3,0.1

Type RM Length L Ch R = 1 ,3938.3  ,1171.9,1158.4,1144.1
XS GIS Cut Line= 5
     1572953.553      238716.561     1572375.428      239279.061
     1572266.053      239404.061     1572115.012      239575.936
     1571958.762      239898.853
#Sta/Elev= 30
       0 1049.39      59 1026.88     118 1006.43   226.2  964.72   285.3  940.06
   304.9  934.05   354.1  924.61   373.8  918.61   491.8  860.44     541  838.52
   570.5   828.7   678.7  803.56   806.6  779.98   884.8  770.46   943.4  765.73
  1058.5  758.64  1087.1   758.3  1096.6   758.3  1125.3   758.3  1153.9  758.83
  1172.9  761.72  1220.9  771.98  1288.8  789.04  1327.6  803.04    1376  825.43
  1443.9  851.51  1482.7  863.57  1531.2  875.71  1550.6   878.7  1560.3  877.94
#Mann= 3 , 0 , 0
       0    .065       0  1096.6    .045       0  1125.3     .08       0
Bank Sta=1096.6,1125.3
XS Rating Curve= 0 ,0
Exp/Cntr=0.3,0.1

Type RM Length L Ch R = 1 ,2779.9  ,1289,1257.4,1225.5
XS GIS Cut Line= 4
     1571943.137       237971.77     1571880.637      238404.061
     1571849.387      238695.728     1571755.637      239466.561
#Sta/Elev= 30
       0 1049.16    38.8 1031.36   126.2  998.06     165  984.13   194.1  974.83
   291.2  949.44   378.6  923.86   388.2  919.08   407.7  907.54   446.6  881.95
   485.7  853.38   563.9  793.73     603  765.98   612.8  760.77   622.6  758.63
   632.3   758.3   671.5   758.3   700.8  759.06   759.6   764.6   848.1  767.57
     907  777.06   985.7  785.73  1074.2  798.26    1143  805.98  1172.4  810.72
  1211.8  821.11    1428   871.1  1447.7  874.38  1467.3  876.42  1506.6  877.61
#Mann= 3 , 0 , 0
       0      .1       0   632.3    .045       0   671.5     .07       0
Bank Sta=632.3,671.5
XS Rating Curve= 0 ,0
Exp/Cntr=0.3,0.1

Type RM Length L Ch R = 1 ,1522.5  ,1384,1389.2,1394.3
XS GIS Cut Line= 5
      1570057.72      239091.561     1570812.928       239409.27
     1571104.595      239492.603     1571385.845      239591.561
     1571844.178      239898.853
#Sta/Elev= 30
       0 1057.13    87.8 1043.81   253.6 1014.71   360.9  992.62   419.4  984.52
     595  945.05   721.8  904.69   741.3  894.69     790  859.49   848.7  824.58
     878  808.77   936.7  782.97   995.4  759.85  1005.2  756.86  1024.8  754.45
  1044.4   754.3  1063.9   754.3  1093.3  755.08  1112.9  758.56  1141.9  760.68
  1170.7  778.48    1190  787.05  1238.1  798.34  1372.7  837.18  1420.8   849.1
  1459.5  855.93  1624.1  864.39  1788.7  867.27  1895.2   865.2  1972.6  855.48
#Mann= 3 , 0 , 0
       0      .1       0  1024.8    .045       0  1063.9      .1       0
Bank Sta=1024.8,1063.9
XS Rating Curve= 0 ,0
Exp/Cntr=0.3,0.1

Type RM Length L Ch R = 1 ,133.3   ,120.6,133.3,143.5
XS GIS Cut Line= 5
     1569936.105      240351.197     1570884.022      240601.197
     1571035.064      240637.655     1571290.272       240778.28
     1571852.772      240991.822
#Sta/Elev= 30
       0  947.42    88.2  913.38   303.9     836   421.5  815.39   617.6  770.34
   656.8  767.18     696   769.9   725.4  766.99   754.8  774.96   774.5  777.74
   892.1  779.52  1135.7  767.59    1194  762.81  1240.9  752.52  1252.3   752.1
  1281.4  752.77  1291.1  756.12    1330  775.39  1388.2  806.64  1465.9   864.6
  1485.3  877.67  1514.4  891.91  1553.2   906.2    1660  923.76  1776.4  952.96
  1805.6  956.52    1825  956.47  1883.2  949.26  1960.8  947.03  2028.8  936.24
#Mann= 3 , 0 , 0
       0     .07       0  1240.9    .045       0  1281.4      .1       0
Bank Sta=1240.9,1281.4
XS Rating Curve= 0 ,0
Exp/Cntr=0.3,0.1

Chan Stop Cuts=-1
Use User Specified Reach Order=0
Composite Channel Slope=5